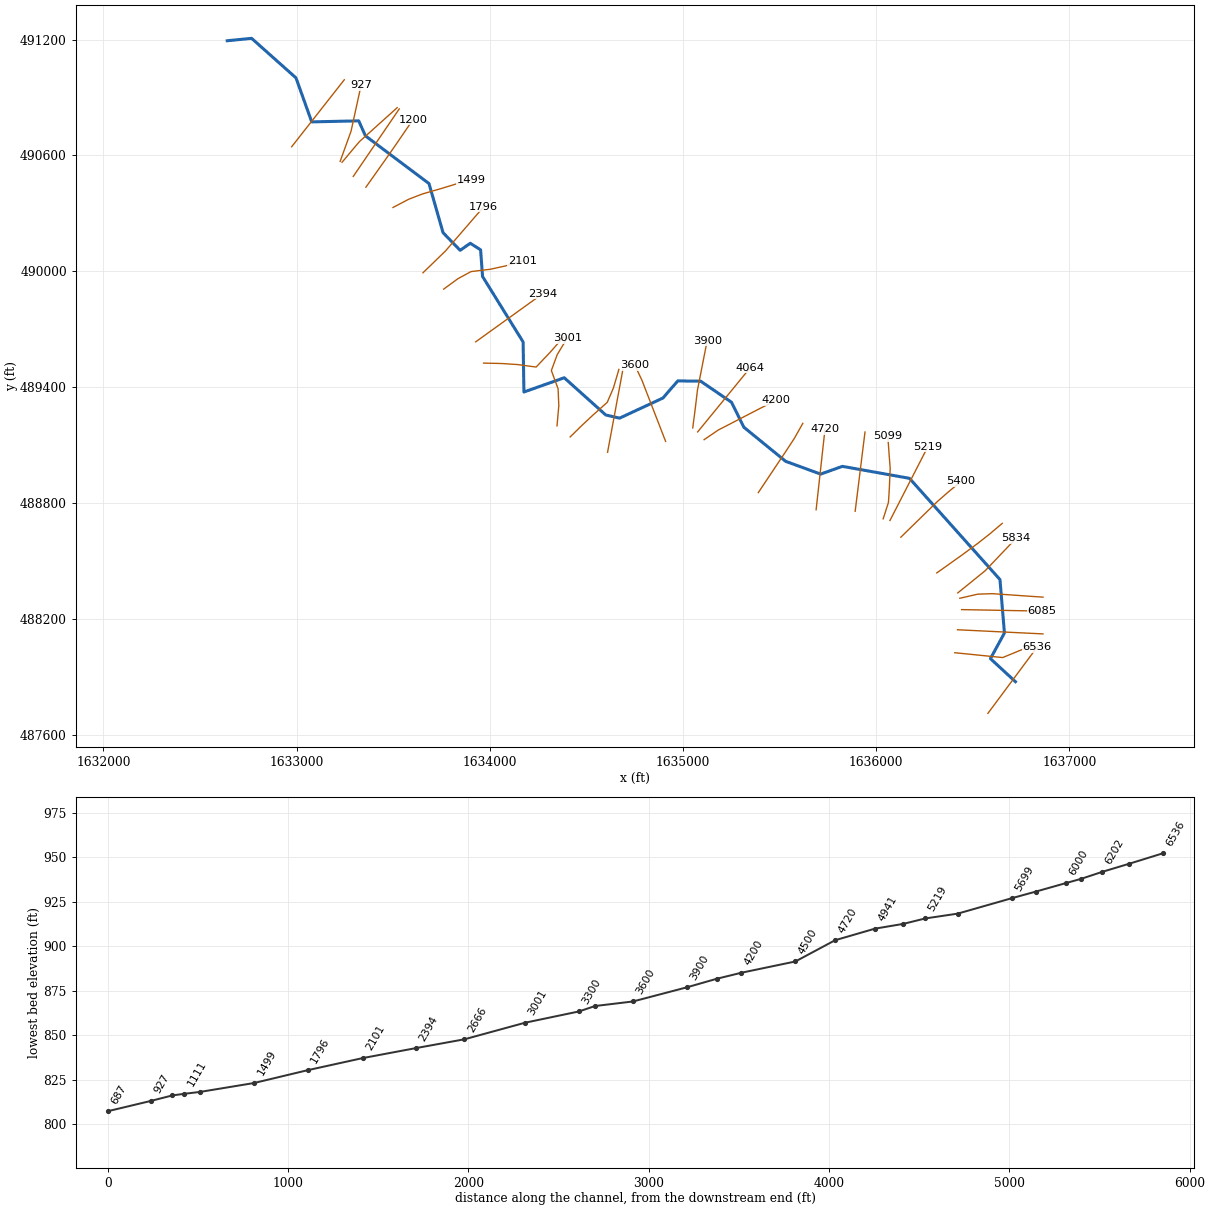
--- GraveCkT3.prj (project) ---

Proj Title=GraveCkT3
Current Plan=p01
Default Exp/Contr=0,0
English Units
Geom File=g01
Flow File=f01
Plan File=p01
BEGIN DESCRIPTION:
---------- MODELED AS PART OF WVEM CTP PROGRAM, 2025----------
Stream Name: Grave Creek Tributary 3
Flood Zone: AFH
Marshall County, WV
HEC-RAS Version: RAS 6.6
Vertical Datum: NAVD88
Projection: NAD 1983 StatePlane West Virginia N FIPS 4701 (US Feet)
Terrain: 1-meter West Virginia FEMA R3 South Central (collected 2018-2019)
Land Use: 2024 NLCD
Hydrologic Method:
Duda et al., "Estimation of magnitude and frequency of floods for rural, unregulated streams in and near Virginia and West Virginia." September 8, 2025.
Additional Model Notes:
None
END DESCRIPTION:
DSS Export Rating Curves= 0
DSS Export Rating Curve Sorted= 0
DSS Export Volume Flow Curves= 0
DXF OffsetX= 0
DXF OffsetY= 0
DXF ScaleX= 0
DXF ScaleY= 0

--- GraveCkT3.p01 (plan) ---

Plan Title=Floodplain
Program Version=6.60
Short Identifier=Floodplain
Geom File=g01
Flow File=f01
Subcritical Flow
K Sum by GR= 0
Std Step Tol= 0.01
Critical Tol= 0.01
Num of Std Step Trials= 20
Max Error Tol= 0.3
Flow Tol Ratio= 0.001
Split Flow NTrial= 30
Split Flow Tol= 0.02
Split Flow Ratio= 0.02
Log Output Level= 0
Friction Slope Method= 1
Unsteady Friction Slope Method= 2
Unsteady Bridges Friction Slope Method= 1
Parabolic Critical Depth
Global Vel Dist= 0 , 0 , 0
Global Log Level= 0
CheckData=False
Encroach Param=-1 ,0,0, 0
Flow Ratio Tolerance=0.1
Flow Ratio Min Ratio=0.5
Flow Ratio Max Ratio=4
Flow Ratio Max Iterations= 10
Mapping Interval=1HOUR
Computation Time Step Use Courant=        0
Computation Time Step Use Time Series=    0
Computation Time Step Count To Double=0
Computation Time Step Max Doubling=0
Computation Time Step Max Halving=0
Computation Time Step Residence Courant=0
Run HTab= 0
Run UNet= 0
Run Sediment= 0
Run PostProcess= 0
Run WQNet= 0
Run RASMapper=-1
UNET Theta= 0
UNET Theta Warmup= 0
UNET ZTol= 0
UNET ZSATol= 0
UNET MxIter= 0
UNET Max Iter WO Improvement= 0
UNET MaxInSteps= 0
UNET DtIC= 0
UNET DtMin= 0
UNET MaxCRTS= 0
UNET WFStab= 0
UNET SFStab= 0
UNET WFX= 1
UNET SFX= 1
UNET Gravity=32.17405
UNET 1D Methodology=Finite Difference
UNET DSS MLevel= 1
UNET Pardiso=0
UNET DZMax Abort= 0
UNET Use Existing IB Tables= 0
UNET Froude Reduction=False
UNET Froude Limit= 0
UNET Froude Power= 0
UNET D1 Cores= 0
UNET WindReference=Eulerian
UNET WindDragFormulation=Hsu (1988)
UNET D2 Coriolis=0
UNET D2 Cores= 0
UNET D2 Theta= 1
UNET D2 Theta Warmup= 1
UNET D2 Z Tol= 0.01
UNET D2 Volume Tol= 0.01
UNET D2 Max Iterations= 20
UNET D2 Advanced Convergence=0
UNET D2 WS Max Tol=0.15
UNET D2 WS RMS Tol=0.002
UNET D2 WS Stall Tol=1
UNET D2 Equation= 0
UNET D2 RampUpFraction=0.1
UNET D2 TimeSlices= 1
UNET D2 Turbulence Formulation=Non-Conservative (original)
UNET D2 Eddy Viscosity=0.3
UNET D2 Transverse Eddy Viscosity=0.1
UNET D2 Smagorinsky Mixing=0
UNET D2 BCVolumeCheck=0
UNET D2 Cores=0
UNET D2 SolverType=PARDISO (Direct)
UNET D2 Minimum Iterations= 3
UNET D2 Maximum Iterations= 30
UNET D2 Restart Number= 10
UNET D2 Relaxation Coeff=1.3
UNET D2 SOR Precondition Iterations= 10
UNET D2 ILUT Maximum Fill= 8
UNET D2 ILUT Tolerance=1E-08
UNET D2 Convergence Tolerance=0.00001
PS Theta= 1
PS WS Tol= 0.01
PS Volume Tol= 0.01
PS Max Iterations= 20
PS Equation= 0
PS Advance Time Step=-1
PS Target Courant=0.9
PS Time Slices= 1
PS Iterate With 2D=0
PS Project Initial WSE from DS=-1
PS Ramp Up Initial WSE from US=-1
PS Cores=0
UNET D1D2 MaxIter= 0
UNET D1D2 ZTol=0.01
UNET D1D2 QTol=0.1
UNET D1D2 MinQTol=1
Write IC File= 0
Write IC File at Fixed DateTime=0
Write IC File at Sim End=0
Echo Input=False
Echo Parameters=False
Echo Output=False
Write Detailed= 0
HDF Write Warmup=0
HDF Write Time Slices=0
HDF Flush=0
HDF Compression= 1
HDF Chunk Size= 1
HDF Spatial Parts= 1
HDF Use Max Rows=0
HDF Fixed Rows= 1
Calibration Method= 0
Calibration Iterations= 20
Calibration Max Change=0.05
Calibration Tolerance=0.2
Calibration Maximum=1.5
Calibration Minimum=0.5
Calibration Optimization Method= 1
WQ AD Non Conservative
WQ ULTIMATE=-1
WQ Max Comp Step=1HOUR
WQ Output Interval=15MIN
WQ Output Selected Increments= 0
WQ Create Restart=0
WQ Fixed Restart=0
WQ System Summary=0
WQ Write To DSS=0
Sorting and Armoring Iterations= 10
XS Update Threshold= 0.02
Bed Roughness Predictor= 0
Processes Affected by Predictor=Sediment Only
Hydraulics Update Threshold= 0.02
Energy Slope Method= 1
Volume Change Method= 1
Sediment Retention Method= 0
Sediment TS Multiplier= 1
Warm Up Method= 0
XS Weighting Method= 0
Number of US Weighted Cross Sections= 1
Number of DS Weighted Cross Sections= 1
Upstream XS Weight=0
Main XS Weight=1
Downstream XS Weight=0
Number of DS XS's Weighted with US Boundary= 1
Upstream Boundary Weight= 1
Weight of XSs Associated with US Boundary= 0
Number of US XS's Weighted with DS Boundary= 1
Downstream Boundary Weight= 0.5
Weight of XSs Associated with DS Boundary= 0.5
Percentile Method= 0
Sediment Output Level= 3
Mass or Volume Output= 0
Output Increment Type= 1
Profile and TS Output Increment= 1
Transport Output Increment 1
XS Output Flag= 0
XS Output Increment= 10
Read HDF5 Sediment Hotstart= 0
Sediment Hotstart Type= 0
Write Gradation File= 0
Read Gradation Hotstart= 0
Write HDF5 File= 1
Write Binary Output= 1
Write DSS Sediment File= 0
DSS Sediment Output Type= 1
SV Curve= 0
Specific Gage Flag= 0
Subcell Erosion Methods= 0
Subcell Deposition Methods= 0
Advection Scheme= 1
Matrix Solver= 0
Implicit Weighting Factor= 1
Maximum Outer Loop Convergence Iterations= 5
Convergence Maximum Absolute= 0.001
Convergence RMSE= 0.0001
Grain Fractions Max Abs Error= 0.001
Max Subgrid Regions= 1
Max Subgrid Length Scale= 3.402823E+38
Initial Layer Thickness= 3
Min Layer Thickness= 0.1
Max Layer Thickness= 6
Number of Layers= 5

--- GraveCkT3.f01 (steady flow) ---

Flow Title=Flow
Program Version=6.60
Number of Profiles= 1
Profile Names=P100yr
River Rch & RM=GraveCkT3,Main            ,6536
     831
River Rch & RM=GraveCkT3,Main            ,2666
     994
Boundary for River Rch & Prof#=GraveCkT3,Main            , 1
Up Type= 0
Dn Type= 3
Dn Slope=0.013913
DSS Import GetInterval= 0
DSS Import GetPeak= 0
DSS Import FillOption= 0

--- GraveCkT3.g01 (geometry) ---

Geom Title=Geometry
Program Version=6.60

River Reach=GraveCkT3       ,Main
Reach XY= 30
     1636720.427      487874.487     1636590.983      487993.986
     1636663.312      488126.552     1636640.276      488403.486
     1636172.128      488927.679     1635824.872      488989.743
     1635712.165      488949.644     1635531.303      489015.683
     1635314.744      489192.381     1635251.085      489321.483
     1635091.045      489430.953     1634972.652      489432.143
     1634895.904      489343.496      1634671.61      489239.381
     1634600.047      489255.805     1634385.205      489448.563
     1634176.546      489374.695     1634172.453      489633.828
     1633962.557      489972.874     1633952.277      490111.092
      1633898.97      490144.979     1633846.424      490108.426
     1633758.087      490199.809     1633685.195      490454.255
     1633356.382      490701.275     1633321.733       490778.95
     1633078.425       490773.62     1632996.846      491001.602
     1632767.198      491206.262     1632641.141      491193.795

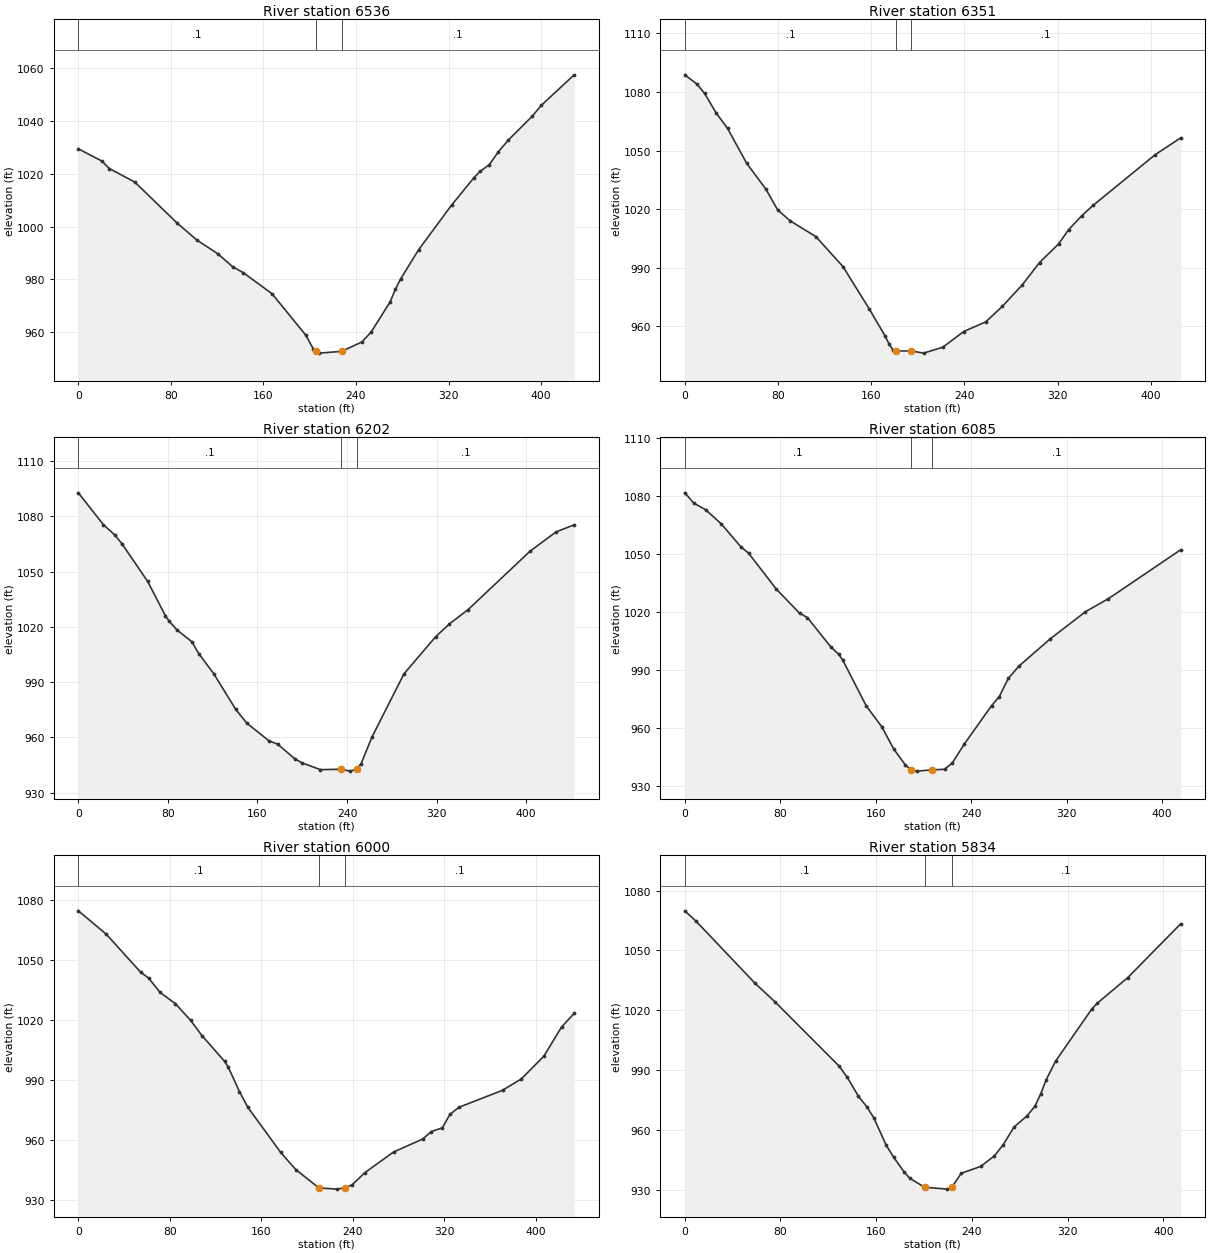
Type RM Length L Ch R = 1 ,6536    ,188.7,184.7,174.2
XS GIS Cut Line= 2
1636577.88864795487710.5412365091636833.37282144488054.612568152
#Sta/Elev= 30
       0  1029.5    20.3 1024.89    26.8 1022.03    48.8 1016.91    85.7 1001.25
   102.8  994.84   120.4   989.8   133.3  984.87   142.7  982.54   167.4  974.63
   196.6  958.93   202.9  953.85  205.47952.7719   208.4   952.1  227.64952.7712
   245.1  956.32   253.2  960.13   269.6  971.58     274  976.23   278.7  980.29
   294.1  991.23   322.7 1008.22     342 1018.57   347.2 1020.94   355.4 1023.55
   363.1  1028.4   371.7 1032.82   392.2 1041.79   400.3 1046.02   428.6 1057.54
#Mann= 3 ,-1,0
       0      .1       0  205.47    .045       0  227.64      .1       0
Bank Sta=205.47,227.64
XS Rating Curve= 0 ,0
Exp/Cntr=0.3,0.1

Type RM Length L Ch R = 1 ,6351    ,146.6,149.6,147.6
XS GIS Cut Line= 3
1636406.40690191488024.630274758 1636654.2649645487999.583731614
1636817.42304523488066.585209803
#Sta/Elev= 30
       0 1088.77    10.4 1084.05      17 1079.23    26.9 1069.27    36.7 1061.35
    53.2 1043.39    69.7 1030.15    79.6 1019.71    90.2 1014.12   112.6 1005.89
   135.7  990.64   158.5  968.72   171.9  955.05   175.2  951.08   178.5   948.1
   181.1  947.41   194.4  947.41   204.9   946.3   221.4  949.32   239.3  957.34
   258.3  962.31   272.5  970.26   289.6  981.24   304.4  992.67   320.7 1002.17
   329.3 1009.46   340.8 1016.71   350.5    1022   403.7 1047.91   425.5 1056.48
#Mann= 3 ,-1,0
       0      .1       0   181.1    .045       0   194.4      .1       0
Bank Sta=181.1,194.4
XS Rating Curve= 0 ,0
Exp/Cntr(USF)=0,0
Exp/Cntr=0.3,0.1

Type RM Length L Ch R = 1 ,6202    ,115.9,116.9,115.3
XS GIS Cut Line= 2
1636420.56036018488143.5876588371636862.87825997488122.068491303
#Sta/Elev= 30
       0  1092.8    22.4 1075.51    32.3 1070.09    38.9 1065.22    61.9 1044.74
    77.8 1026.04      81  1023.2    88.1 1018.38   101.3 1012.03   107.8 1005.32
     121  994.57   140.5  975.32   150.5  967.77   170.2   958.2   178.1  956.34
   193.2   948.5   199.6  946.27   216.2  942.54  234.86  942.76   242.5  941.74
  248.62942.7518   252.4  945.59   262.2  960.22   290.8  994.53     319 1014.63
   331.2 1021.54   348.1 1029.42   403.3 1061.06   426.5 1071.53   442.8 1075.45
#Mann= 3 ,-1,0
       0      .1       0  234.86    .045       0  248.62      .1       0
Bank Sta=234.86,248.62
XS Rating Curve= 0 ,0
Exp/Cntr(USF)=0,0
Exp/Cntr=0.3,0.1

Type RM Length L Ch R = 1 ,6085    ,84.3,84.7,83.9
XS GIS Cut Line= 2
1636441.96193161 488247.91586127 1636857.2446785488240.093754737
#Sta/Elev= 30
       0 1081.83     7.6 1076.48    17.4 1073.12    30.5  1065.8    46.9 1053.97
    53.5 1050.58    76.5 1032.13    96.2 1019.51   102.7 1017.29   122.4 1002.04
     129  998.24   132.3  995.29     152   971.6   165.1  960.72   174.9  949.39
   184.8  940.99  189.51  938.49   194.6  937.81  207.43  938.49   217.6  938.76
   224.1  942.03     234  951.68     257  971.69   263.5   976.4     271  985.76
   279.9  992.15   306.2 1006.27   335.7 1020.32   354.7 1026.97   415.4 1052.34
#Mann= 3 ,-1,0
       0      .1       0  189.51    .045       0  207.43      .1       0
Bank Sta=189.51,207.43
XS Rating Curve= 0 ,0
Exp/Cntr(USF)=0,0
Exp/Cntr=0.3,0.1

Type RM Length L Ch R = 1 ,6000    ,155.2,166.4,175.4
XS GIS Cut Line= 6
 1636432.3254285488306.6326083391636524.98502009488327.828760177
1636601.16793859488330.4678625021636700.93086243488323.587626919
1636775.75321934488318.4262199251636863.04569568488312.405562669
#Sta/Elev= 30
       0 1074.38    24.4 1062.75    54.7 1043.62    61.4 1040.86    71.5 1033.65
      85 1027.98    98.3 1019.65   108.2 1012.06   127.9  999.26   131.2  996.31
     141  984.07   148.4   976.2   177.1  953.71   190.3  945.15  210.45936.0518
   225.9  935.42  233.58936.0512   239.6  937.62   250.5  943.57   275.8  953.95
   301.3  960.44   308.7  964.14   318.5  966.06   325.1  972.76     333  976.28
   371.2  984.79   387.6  990.46   407.3  1001.8   422.8 1016.38   433.8 1023.21
#Mann= 3 ,-1,0
       0      .1       0  210.45    .045       0  233.58      .1       0
Bank Sta=210.45,233.58
XS Rating Curve= 0 ,0
Exp/Cntr(USF)=0,0
Exp/Cntr=0.3,0.1

Type RM Length L Ch R = 1 ,5834    ,136.2,134.5,131.8
XS GIS Cut Line= 3
1636422.01491506488334.4091475721636563.44492209488448.975354381
1636723.83761162488617.269161626
#Sta/Elev= 30
       0 1069.84     9.5  1064.6    58.8 1033.57    75.1 1024.49   128.8  992.34
   135.8  986.59   145.1  977.14   152.1  971.88   157.9  966.42   168.4  952.57
   174.7  946.51   183.3  939.27   188.1  936.06  200.53931.5847   219.5  930.65
  223.25  931.58   231.1  938.56   247.4  942.04   258.6  947.15     266  952.71
   275.2  961.68   285.8  967.15   292.7  972.05   297.5  978.24   302.2  985.47
     310  994.67   340.2 1020.71     345 1023.73   370.4 1036.49   414.5 1063.32
#Mann= 3 ,-1,0
       0      .1       0  200.53    .045       0  223.25      .1       0
Bank Sta=200.53,223.25
XS Rating Curve= 0 ,0
Exp/Cntr(USF)=0,0
Exp/Cntr=0.3,0.1

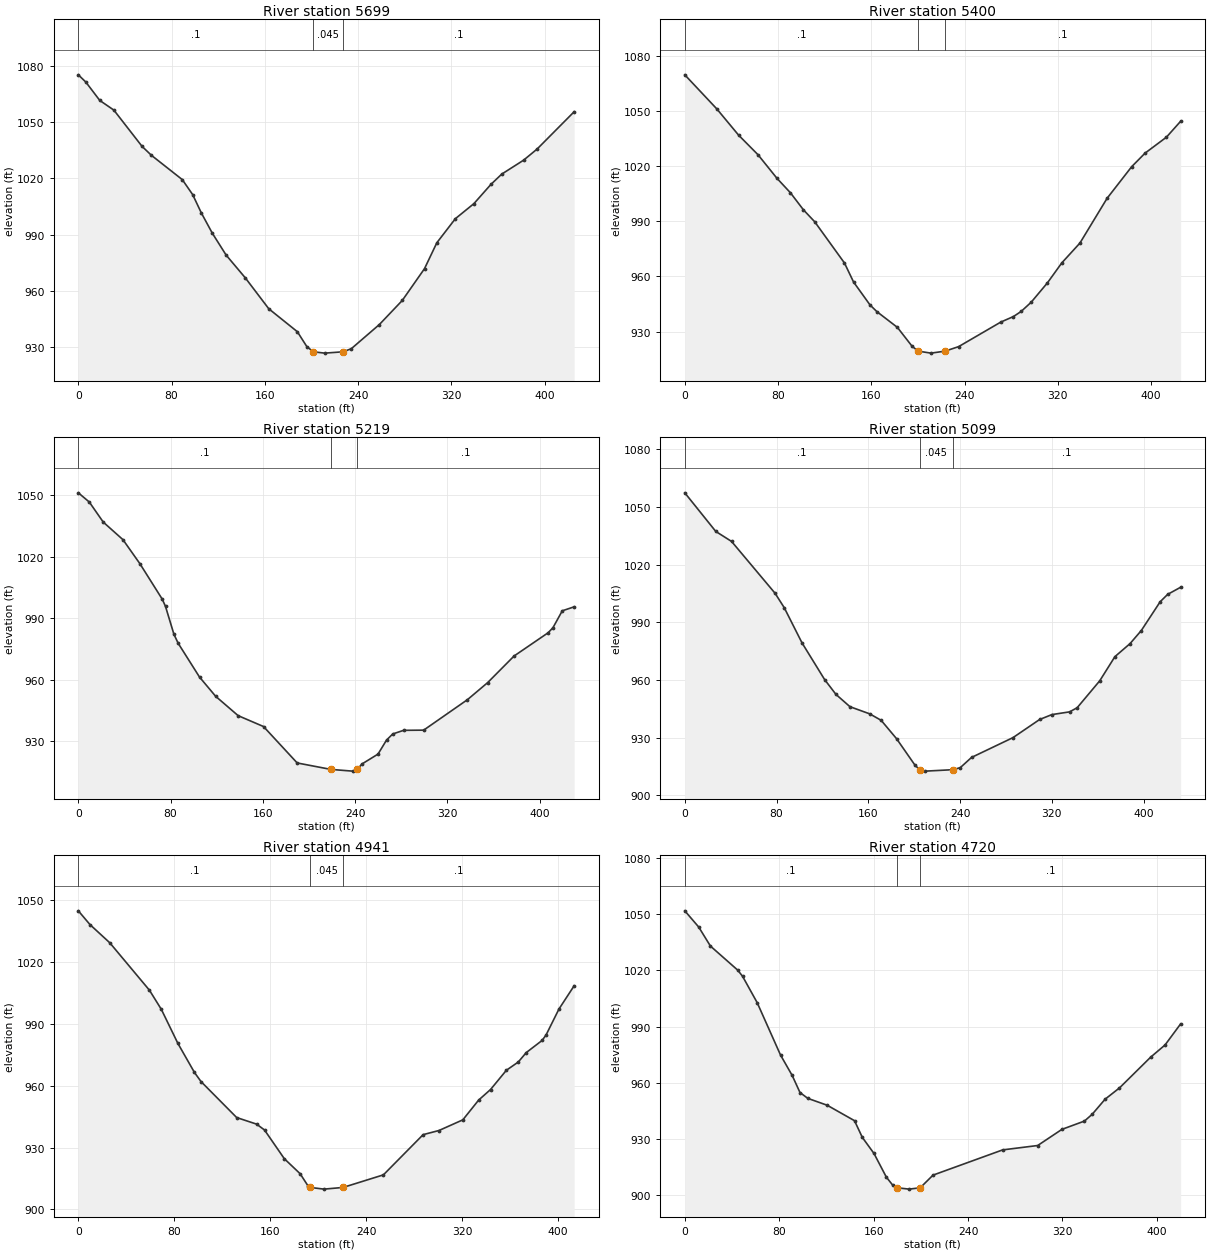
Type RM Length L Ch R = 1 ,5699    ,296.7,299.1,300.1
XS GIS Cut Line= 6
1636313.11175618488437.7402857541636384.42099676488488.447861508
1636445.54226559488531.9126695841636526.00765584488591.313797504
1636584.99113367488637.7845050841636652.02446418488694.505520254
#Sta/Elev= 30
       0 1075.11     6.4 1071.28    18.4 1061.47    30.5 1056.31    54.7 1036.99
    62.7 1032.25    89.2  1019.3    98.1 1011.32   105.6 1001.48     115  990.72
   126.8  979.12   143.3  966.95   163.4  950.52   187.9  938.31     196  930.42
  201.64927.6034   211.4   926.9  227.11927.6043   234.2  929.25   258.3  942.14
   277.9  954.93     297  971.88   307.6  985.69   323.5  998.51   339.4 1006.52
     354 1016.76   363.3 1022.25     382 1029.65   393.6 1035.58   425.4 1055.46
#Mann= 3 ,-1,0
       0      .1       0  201.64    .045       0  227.11      .1       0
Bank Sta=201.64,227.11
XS Rating Curve= 0 ,0
Exp/Cntr(USF)=0,0
Exp/Cntr=0.3,0.1

Type RM Length L Ch R = 1 ,5400    ,173.4,180.7,180.6
XS GIS Cut Line= 6
1636127.36311193488622.996476918 1636189.9423831488684.152522594
1636243.58236767488736.5717090821636315.10190967488806.463957757
1636371.52305667488856.0373494181636439.22698951488911.859088168
#Sta/Elev= 30
       0 1069.81    27.5 1051.23    46.2 1036.93    62.8  1026.3    79.1 1013.44
    90.6  1005.6   101.8  996.28   111.5  989.76     137  967.32   144.8  956.97
   158.9   944.5   164.8  940.85   182.4  932.27     195     922  200.22919.3333
   211.2  918.25  223.32919.3337   234.9  921.78   271.1  935.15     282  938.19
   288.6  940.96   297.2  945.98   311.1   956.5   323.5  967.43     339  978.18
   362.3 1002.56   383.4 1019.78   394.9 1027.17   413.2 1035.84   425.4 1044.51
#Mann= 3 ,-1,0
       0      .1       0  200.22    .045       0  223.32      .1       0
Bank Sta=200.22,223.32
XS Rating Curve= 0 ,0
Exp/Cntr(USF)=0,0
Exp/Cntr=0.3,0.1

Type RM Length L Ch R = 1 ,5219    ,110.7,120.3,121
XS GIS Cut Line= 2
1636070.96825517488709.4752053131636267.23201911 489092.04732488
#Sta/Elev= 30
       0 1051.15     9.5 1046.67    21.6 1036.89    38.7 1028.32    53.4 1016.61
    72.8   999.3    75.6  995.79    82.9  982.22    86.6  977.82   105.1  961.36
   119.1  951.99   138.6  942.56   160.6  937.26   189.8  919.51  219.07916.3638
   237.8  915.53  241.97 916.363   245.9  918.99   259.9  923.83   267.3  930.67
   272.7  933.65   282.1  935.41   299.5   935.5   337.4  950.33     355  958.67
   377.9  971.63   407.4  982.95   411.6  985.41   419.7  993.66     430   995.6
#Mann= 3 ,-1,0
       0      .1       0  219.07    .045       0  241.97      .1       0
Bank Sta=219.07,241.97
XS Rating Curve= 0 ,0
Exp/Cntr(USF)=0,0
Exp/Cntr=0.3,0.1

Type RM Length L Ch R = 1 ,5099    ,158.2,157.8,155.8
XS GIS Cut Line= 6
1636035.87477784488718.2085568461636063.16245292488803.105368674
1636067.84059317488877.9592215871636072.13225126488978.640122592
1636066.24020268489055.9237606671636059.89769568489145.565313667
#Sta/Elev= 30
       0 1057.38      27 1037.29    40.8 1032.07    78.7  1005.1    86.7  997.59
   102.2  979.26   121.9  960.17   131.8  952.44     144  946.04   161.3   942.3
   171.2  938.95   184.6  929.41   200.8  915.51   204.8 913.251   209.8   912.5
  233.91913.2514   240.2  914.32     250  919.63   286.2  929.96   309.4  939.39
   320.1  941.94   335.5  943.35   342.1  945.51   361.8  959.54     375  972.09
   388.2  978.88     398  985.68   414.5  1000.7     421 1004.52   432.3 1008.22
#Mann= 3 ,-1,0
       0      .1       0   204.8    .045       0  233.91      .1       0
Bank Sta=204.8,233.91
XS Rating Curve= 0 ,0
Exp/Cntr(USF)=0,0
Exp/Cntr=0.3,0.1

Type RM Length L Ch R = 1 ,4941    ,219.6,221,220.4
XS GIS Cut Line= 2
1635890.90700442488757.2345935541635941.73980491489167.444105255
#Sta/Elev= 30
       0 1044.98     9.7  1038.3    26.2 1029.47    59.3  1006.4    69.2  997.11
      83  980.57    96.8  966.47   102.3  962.03     132  944.57   148.6  941.38
   155.2  938.53   171.7  924.59   184.9  917.28   191.5  911.33  193.27910.6318
   204.8  909.81   220.7  910.63   254.3  916.74   287.4  936.27   300.6  938.28
   320.5  943.46   333.7  953.07   343.6  958.19   356.8  967.54   366.7  971.54
   373.4  976.14   386.6  982.04   389.9   984.7   400.6  997.25   413.3 1008.59
#Mann= 3 ,-1,0
       0      .1       0  193.27    .045       0   220.7      .1       0
Bank Sta=193.27,220.7
XS Rating Curve= 0 ,0
Exp/Cntr(USF)=0,0
Exp/Cntr=0.3,0.1

Type RM Length L Ch R = 1 ,4720    ,224.3,220.2,211.4
XS GIS Cut Line= 2
1635688.81752854488764.958609684 1635734.7493595 489182.53268071
#Sta/Elev= 30
       0 1051.84    11.8 1043.18    21.7 1033.04    44.8 1020.21    48.9 1016.94
    61.3 1002.86    81.1  974.88      91  963.95    97.6  954.86   104.2  951.75
   120.7  948.06   143.8  939.82   150.4  930.92   160.3  922.33   170.8  909.67
   176.1  905.47  179.86 904.016   190.1   903.3  199.46904.0153   210.3  910.77
   269.3  924.24     299  926.58   319.5  935.19   338.6  939.62   345.2  943.26
   356.1  951.29   368.3  957.32   394.7  973.73   406.9  980.24   420.1  991.49
#Mann= 3 ,-1,0
       0      .1       0  179.86    .045       0  199.46      .1       0
Bank Sta=179.86,199.46
XS Rating Curve= 0 ,0
Exp/Cntr(USF)=0,0
Exp/Cntr=0.3,0.1

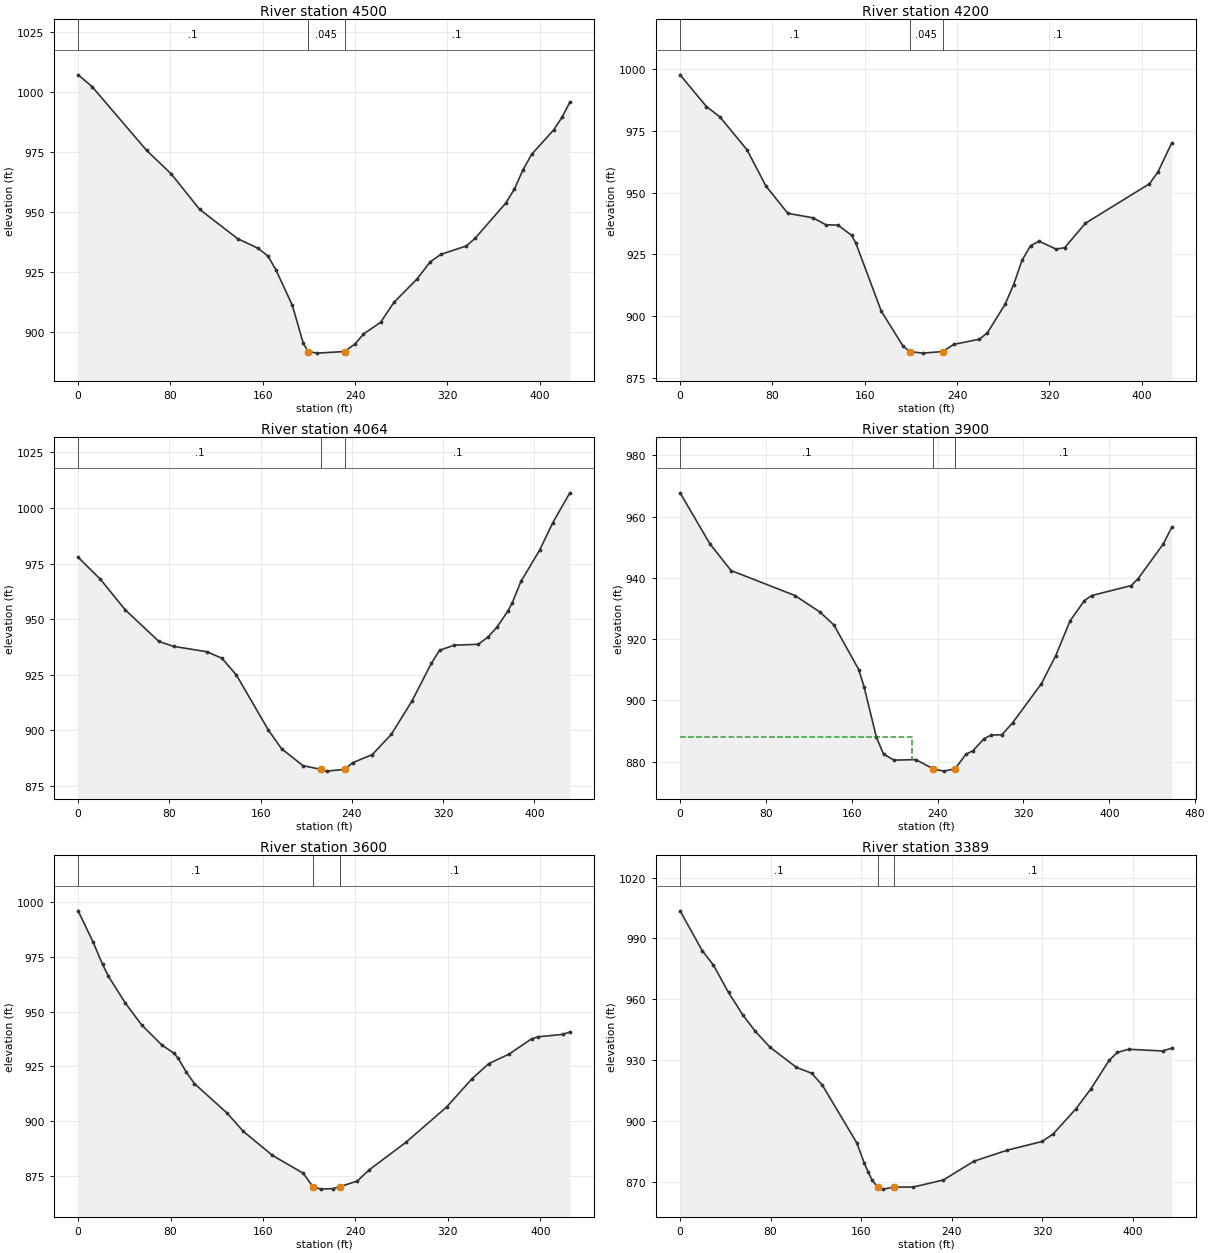
Type RM Length L Ch R = 1 ,4500    ,306.7,300,291.8
XS GIS Cut Line= 6
1635389.69857676488853.8989022521635438.23555318  488926.7028905
1635479.83848834488989.1063090121635535.30950601489072.310867012
1635576.37569684489135.0718963441635619.84411384489212.348972753
#Sta/Elev= 30
       0 1007.14    12.1 1002.24    59.4  975.68    80.7  965.93   105.3  951.16
   138.4  938.93   155.6  935.09   164.5   931.8   171.6  925.86   185.7  911.19
   195.2  895.37  199.36  892.03   207.2  891.36   230.9  892.03   240.2  895.26
   247.3  899.28   262.1  904.16   273.9  912.57   293.5  922.07   305.2  929.35
   314.4  932.44   336.6  935.97   344.2  939.21   370.5  953.68     378   959.5
   385.6  967.62   393.1  974.08   412.1   984.2   419.5  989.54   426.2  995.78
#Mann= 3 ,-1,0
       0      .1       0  199.36    .045       0   230.9      .1       0
Bank Sta=199.36,230.9
XS Rating Curve= 0 ,0
Exp/Cntr(USF)=0,0
Exp/Cntr=0.3,0.1

Type RM Length L Ch R = 1 ,4200    ,129.1,135.5,138.7
XS GIS Cut Line= 6
1635109.16337667489128.0538657611635182.06907076 489177.57542026
1635248.66867509489212.0641964231635337.46803817489258.049996838
1635404.06797059489292.5381168431635482.63703917 489331.85660775
#Sta/Elev= 30
       0  997.74    22.8  984.91    34.5  980.69    57.9  967.43    74.3  952.76
    93.3  941.63   115.2  939.82   126.3  937.01   136.8  936.86   148.5  932.78
   152.2  929.65   174.3  902.03   193.1  887.89   198.9885.6484   210.2  885.01
   227.5885.6491   237.1  888.56   259.3  890.64   266.2  893.22   281.5  904.76
   288.9  912.69   296.2  922.56   303.6  928.53     311  930.33   325.8  927.15
   333.2  927.73   351.1   937.6   406.6   953.6   413.9  958.33     426  970.21
#Mann= 3 ,-1,0
       0      .1       0   198.9    .045       0   227.5      .1       0
Bank Sta=198.9,227.5
XS Rating Curve= 0 ,0
Exp/Cntr(USF)=0,0
Exp/Cntr=0.3,0.1

Type RM Length L Ch R = 1 ,4064    ,159.1,164.5,169.2
XS GIS Cut Line= 2
1635075.61178299489168.0824143191635348.67441108  489501.5885929
#Sta/Elev= 30
       0  977.87    19.6  967.93    41.2  954.25    70.8  939.99    83.6  937.79
     113  935.34     126  932.44   138.7  924.91   166.7  900.17   178.3  891.73
     197  884.14  212.62882.4485   217.9  881.65  233.61 882.448   240.5  885.41
   257.8  889.09   274.4  898.13   292.5  913.09   309.6  930.14   316.8     936
   329.5  938.31   350.7  938.71   359.2  941.96   367.2  946.46   376.9  953.88
   380.4  957.24   388.1  966.97   404.5  981.07   416.1  993.47     431 1006.85
#Mann= 3 ,-1,0
       0      .1       0  212.62    .045       0  233.61      .1       0
Bank Sta=212.62,233.61
XS Rating Curve= 0 ,0
Exp/Cntr(USF)=0,0
Exp/Cntr=0.3,0.1

Type RM Length L Ch R = 1 ,3900    ,293.5,300,304.1
XS GIS Cut Line= 6
1635050.38790368489188.8988884241635064.51812476489299.265793666
1635074.45675318489383.2534865891635093.69752835489481.384852007
1635108.12892993489554.9834580871635124.96551043489640.848443836
#Sta/Elev= 30
       0  967.76    27.7  951.15    47.5  942.39     107  934.23   130.2  928.87
   143.4   924.6   166.5  910.04   171.5  904.38     183  887.91   189.6  882.46
   199.3  880.48   219.7  880.64  236.04877.6146   245.7  876.88  256.14 877.614
   266.5  882.39   273.1  883.59   283.2  887.44   289.9  888.66   299.9  888.76
   309.9  892.66   336.7  905.42     350   914.5   363.4  925.91   376.8  932.56
   383.5  934.21   420.4  937.46   426.9  939.75   450.3  951.04   458.3  956.54
#Mann= 3 ,-1,0
       0      .1       0  236.04    .045       0  256.14      .1       0
#XS Ineff= 2 , 0
          215.88  887.99
Permanent Ineff=
       F       F
Bank Sta=236.04,256.14
XS Rating Curve= 0 ,0
Exp/Cntr(USF)=0,0
Exp/Cntr=0.3,0.1

Type RM Length L Ch R = 1 ,3600    ,214.1,210.8,207
XS GIS Cut Line= 6
1634909.85504825 489119.111954511634878.26751301489200.711528838
1634851.19342017489270.6543023441634815.09309867489363.910677508
1634788.01966201489433.8537790921634750.70215134489513.677766427
#Sta/Elev= 30
       0  996.19    12.8  982.08    21.1  971.75    26.2   966.3    40.9  953.96
      55  943.98    72.6  934.75    83.1  931.02    86.7  928.66    93.7  922.38
   100.7  917.14   128.9   903.7     143   895.3   168.2  884.32   194.8  876.16
  203.22870.0178   209.8  868.89   220.4  869.13   226.6  870.02   241.5  872.57
     252  877.74   283.7   890.3   318.9  906.43   340.6  919.21   355.4   926.3
   372.7  930.58   392.4  937.61     398  938.57   419.6  939.66   425.6  940.81
#Mann= 3 ,-1,0
       0      .1       0  203.22    .045       0   226.6      .1       0
Bank Sta=203.22,226.6
XS Rating Curve= 0 ,0
Exp/Cntr(USF)=0,0
Exp/Cntr=0.3,0.1

Type RM Length L Ch R = 1 ,3389    ,95.5,89,83.1
XS GIS Cut Line= 2
1634609.52484922489062.6815040541634688.53602633489490.131972219
#Sta/Elev= 30
       0 1003.57    19.5     984    29.5  976.78    42.8   963.3    55.4  952.31
    66.2  944.33    79.5  936.31   102.9  926.36   116.2   923.5   125.8  917.58
   156.3  889.04   162.9     879   166.3  874.76   169.6   870.9  174.64  867.34
   179.6  866.32  188.99867.3412   206.3  867.36   232.8  870.84   259.7  880.08
   289.1  885.51   320.1  889.83   329.8  893.51   349.8  905.83   363.1  915.72
   379.2  929.77   386.5  933.75   396.5   935.3   426.5  934.45   434.7  935.86
#Mann= 3 ,-1,0
       0      .1       0  174.64    .045       0  188.99      .1       0
Bank Sta=174.64,188.99
XS Rating Curve= 0 ,0
Exp/Cntr(USF)=0,0
Exp/Cntr=0.3,0.1

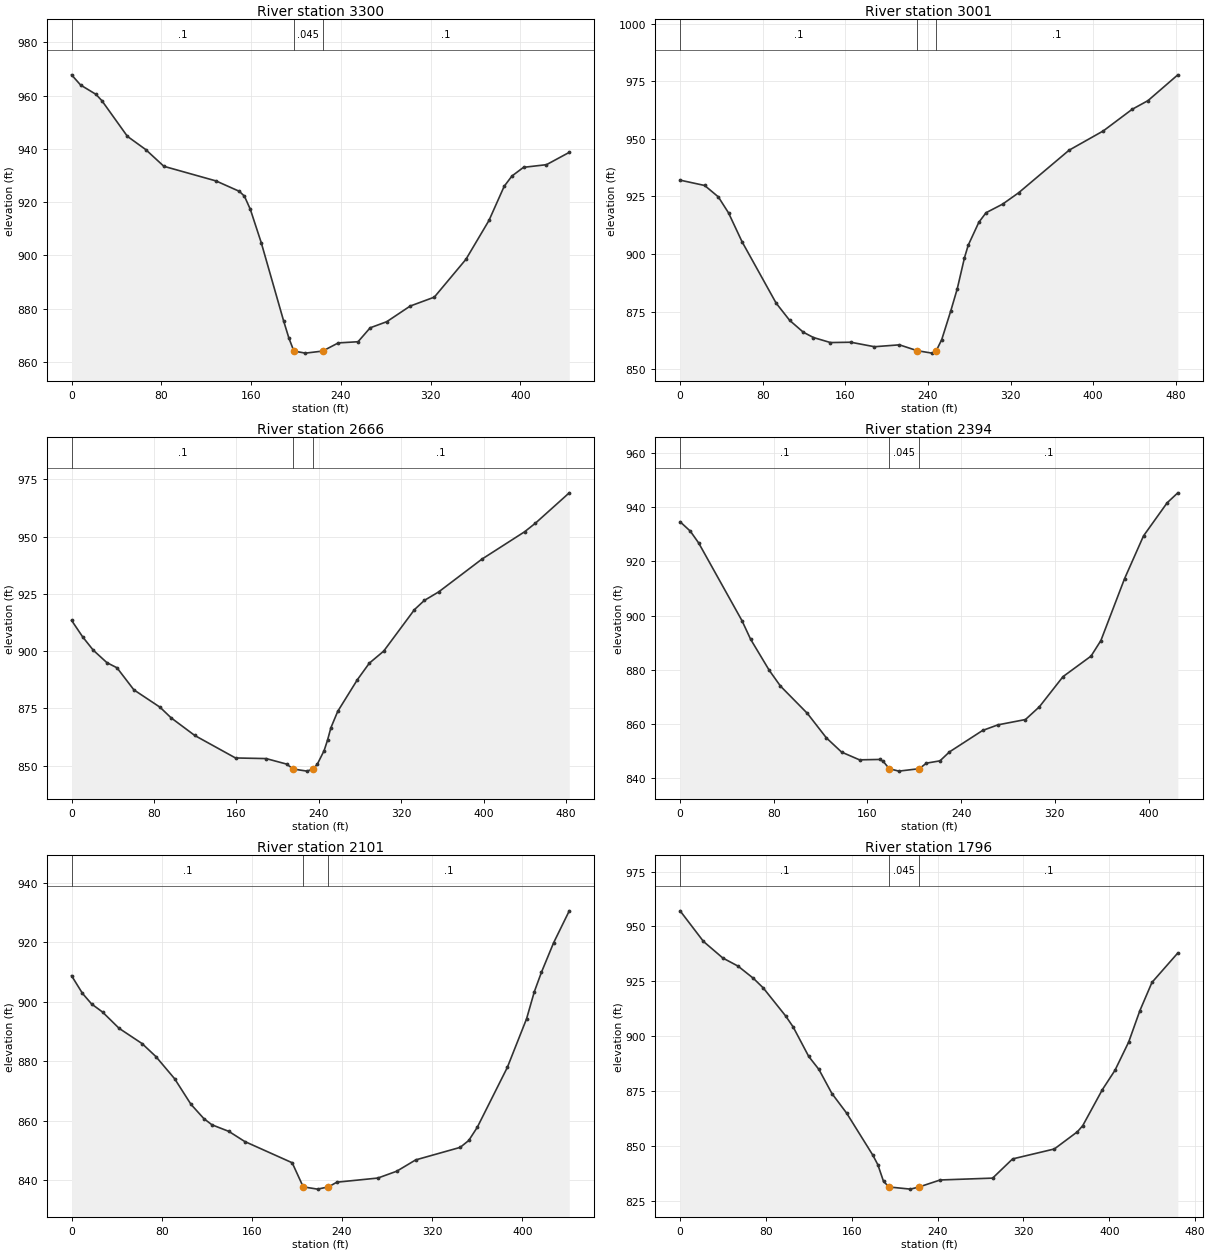
Type RM Length L Ch R = 1 ,3300    ,281.6,299.3,305.7
XS GIS Cut Line= 6
1634415.86620684 489142.123391421634478.44679034 489203.44151026
1634533.25803243489254.6720508341634607.80217467489321.330710173
1634639.70302951489395.3686198441634668.07337959489491.724726334
#Sta/Elev= 30
       0  967.85     8.1  964.01    21.7  960.53      27  958.16    49.8  944.73
    66.1  939.77    82.3  933.48   128.8  927.98   149.6  924.07   154.1  922.26
   159.4  917.28   169.1  904.79   189.1  875.32   193.8  868.87   198.2  864.05
   208.5  863.28  223.83864.0508   237.8  867.12   255.4  867.56   266.2  872.79
     281  875.09   301.9  880.97   323.4  884.32   351.6  898.54   372.1  913.12
   385.7  925.98   392.6  929.83   402.9  933.09   423.4  934.09   443.7  938.72
#Mann= 3 ,-1,0
       0      .1       0   198.2    .045       0  223.83      .1       0
Bank Sta=198.2,223.83
XS Rating Curve= 0 ,0
Exp/Cntr(USF)=0,0
Exp/Cntr=0.3,0.1

Type RM Length L Ch R = 1 ,3001    ,357.5,335.4,320
XS GIS Cut Line= 6
   1634347.80007489199.1885659991634357.14421143489304.281859756
1634353.42440259489391.3699401771634318.56423609 489485.98687692
1634348.82893933489568.3052818331634401.11820485489654.423876002
#Sta/Elev= 30
       0  932.03    23.8  929.71      37  924.77    46.9  917.82      60  905.28
      93  878.64   106.1  871.16   119.3  866.02   129.1  863.71   145.6  861.52
   165.3  861.66   188.2  859.71   212.4  860.53   229.6857.9934   243.9  856.93
  248.11857.9927   253.4  862.84   262.2  875.37   268.4  884.85   275.4  898.34
     279  903.76   289.3  913.73   296.3  917.89   312.3  921.61   327.8  926.53
   376.7  945.03   409.9  953.42   437.7  962.76   453.1  966.55     482  977.75
#Mann= 3 ,-1,0
       0      .1       0   229.6    .045       0  248.11      .1       0
Bank Sta=229.6,248.11
XS Rating Curve= 0 ,0
Exp/Cntr(USF)=0,0
Exp/Cntr=0.3,0.1

Type RM Length L Ch R = 1 ,2666    ,262.7,271.5,278.2
XS GIS Cut Line= 6
1633967.79328409489524.4595690071634063.70254108489522.231555089
1634145.59371734489516.7597848681634239.69136234489503.980607346
 1634309.3926665489577.3019829991634381.40006842489658.922226593
#Sta/Elev= 30
       0  913.49    10.8  906.25    21.1  900.43    34.3  895.01    44.1  892.76
    60.5  883.12    85.8  875.56    96.6  870.91   119.6  863.19   159.1  853.38
   188.8  853.11   208.6  850.72   215.2 848.545   228.5  847.63  234.26 848.544
   238.4  850.57   245.1   856.6   248.4  861.15   251.7   866.6   258.3  873.73
   277.4  887.58     289   894.8   302.9  900.03   332.8  918.18   342.3  922.16
   356.3  925.91   398.1  940.17   439.7  952.18   450.1  955.89     483  969.17
#Mann= 3 ,-1,0
       0      .1       0   215.2    .045       0  234.26      .1       0
Bank Sta=215.2,234.26
XS Rating Curve= 0 ,0
Exp/Cntr(USF)=0,0
Exp/Cntr=0.3,0.1

Type RM Length L Ch R = 1 ,2394    ,299,293,287.3
XS GIS Cut Line= 6
1633926.89781003489634.5003844821633997.94097503489685.587552654
 1634058.8391472 489729.379787911634139.99252819489787.810773405
1634200.87593661489831.5925099881634271.91188377489882.674428823
#Sta/Elev= 30
       0  934.62     8.7  931.16    15.8  926.83    52.8  898.16    60.2  891.29
    76.1  879.83    85.7     874   108.7  863.92   124.9   854.9   137.9  849.65
   153.2  846.79   170.3  846.94   173.4  846.27  178.55 843.535   186.8  842.63
  204.28843.5358   210.3  845.57   221.9  846.42     230  849.72   258.3  857.63
   271.4   859.7   294.9  861.66   306.8  866.37     327   877.5   350.9  885.06
   359.3  890.79   379.5   913.6   395.7   929.4   415.9  941.62     425  945.29
#Mann= 3 ,-1,0
       0      .1       0  178.55    .045       0  204.28      .1       0
Bank Sta=178.55,204.28
XS Rating Curve= 0 ,0
Exp/Cntr(USF)=0,0
Exp/Cntr=0.3,0.1

Type RM Length L Ch R = 1 ,2101    ,286.6,305.5,307.8
XS GIS Cut Line= 6
1633761.29369709489907.5683828441633835.11868067489961.647999093
1633903.07097259489998.4126893431634003.02287242490010.479594335
1634080.89804475490027.6091532561634169.59865476490053.847289756
#Sta/Elev= 30
       0  908.77     9.7  902.83    17.8  899.27    27.5  896.56    42.2  891.09
    62.6  885.96    74.8  881.62    91.5  874.14     106  865.54   117.4  860.76
   124.6  858.67   139.6  856.46   153.7  853.06   195.8  845.92  205.59837.8181
   218.3  837.06  228.01837.8173   235.4  839.39   271.8  840.78   288.6  843.08
   305.4  846.88   344.9  851.09   352.5  853.41   360.1  857.86   386.7  877.93
   403.8  894.29   410.7   903.4     417  909.92   427.8  919.83   441.7  930.57
#Mann= 3 ,-1,0
       0      .1       0  205.59    .045       0  228.01      .1       0
Bank Sta=205.59,228.01
XS Rating Curve= 0 ,0
Exp/Cntr(USF)=0,0
Exp/Cntr=0.3,0.1

Type RM Length L Ch R = 1 ,1796    ,305.8,296.4,290.3
XS GIS Cut Line= 4
1633654.39528884489992.4471500961633717.26950692490053.294141263
1633771.06500301490105.5535511671633968.09355173490333.606323995
#Sta/Elev= 30
       0   957.1    21.8  943.13    39.8   935.6      54   931.9    68.3  926.34
    77.5  921.96    98.4  909.17   105.4  904.15   119.9  890.72   129.4  884.79
   141.5  873.83   155.2  864.91   179.7  845.68   184.3  841.39   189.6  833.78
  194.78831.2292   214.7  830.25  222.69831.2289   242.4  834.42   291.3  835.27
   309.9  844.02   348.8  848.55   370.3  856.39   375.3   859.2   393.6  875.62
   405.3  884.39   418.1   897.3   428.5  911.56   439.8  924.47   463.9  937.89
#Mann= 3 ,-1,0
       0      .1       0  194.78    .045       0  222.69      .1       0
Bank Sta=194.78,222.69
XS Rating Curve= 0 ,0
Exp/Cntr(USF)=0,0
Exp/Cntr=0.3,0.1

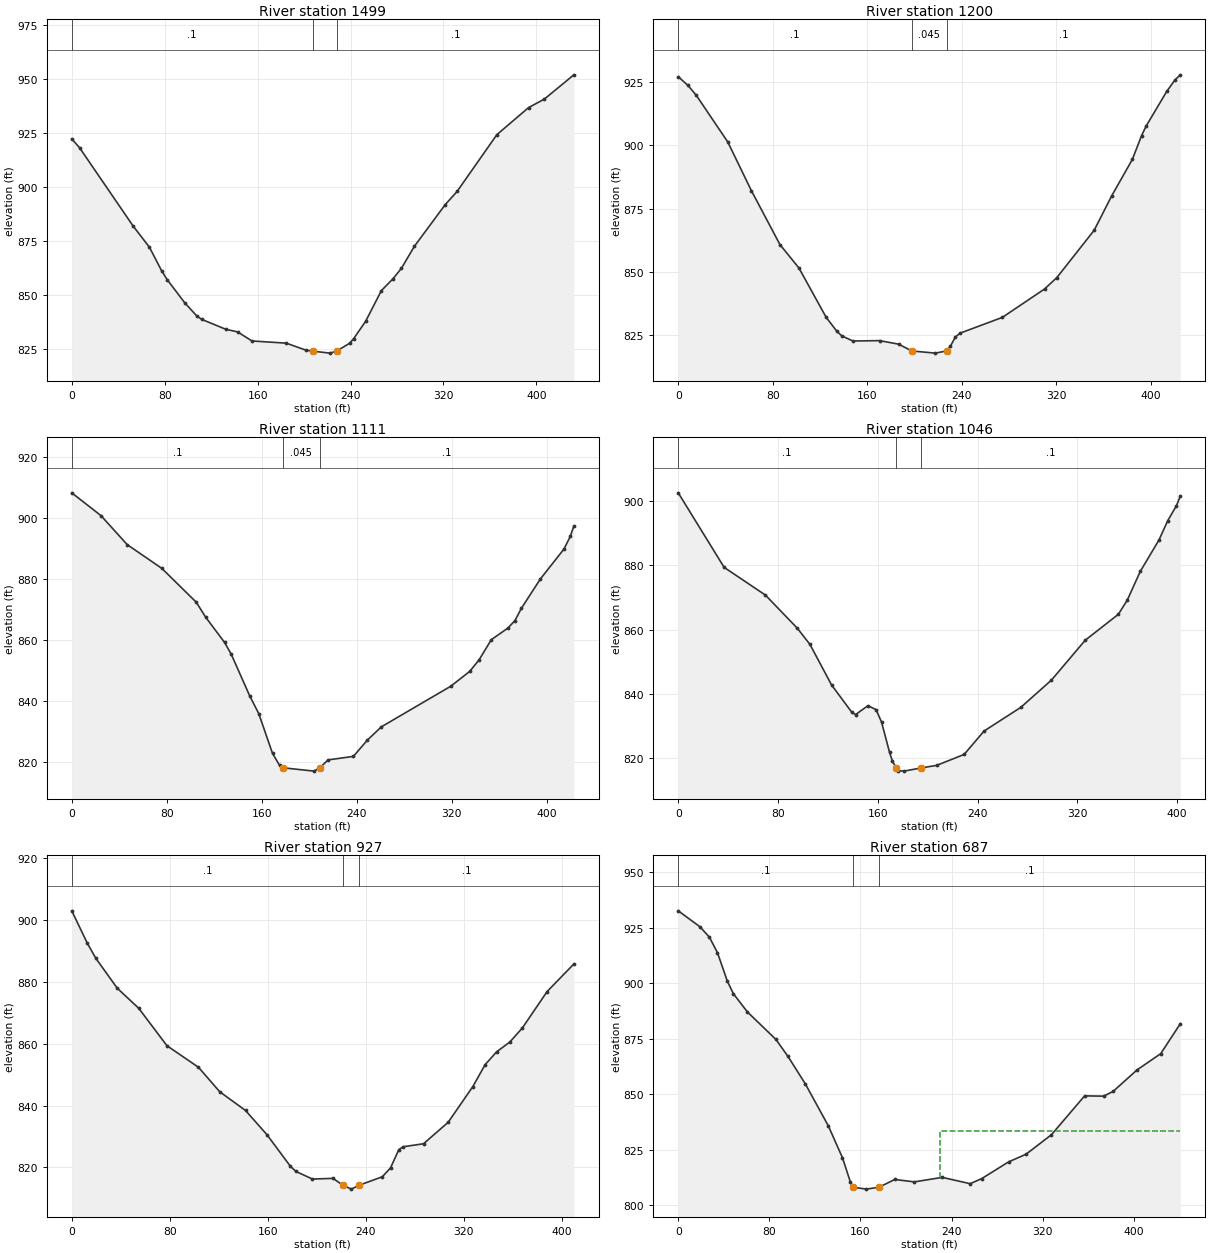
Type RM Length L Ch R = 1 ,1499    ,290.6,299.6,305.5
XS GIS Cut Line= 6
1633498.98910359490330.3588758411633581.13395242490373.297766343
1633653.13249609490400.9545351711633749.23138526490428.658548012
1633820.95794784490450.574514672 1633905.0706405490474.684374586
#Sta/Elev= 30
       0  922.22     6.8  918.02    52.9   881.8    66.9  872.03    77.3  861.23
    82.1   857.1    97.3  846.32   107.8  840.17   112.1  838.63   132.4  834.14
   142.9  832.85   155.1  828.69   184.7  827.67   201.8  824.39  207.38 823.978
   222.2  823.06  228.09823.9776   239.3  827.66   242.7  829.76     253  837.76
   266.6     852   276.5  857.43   283.8  862.27   294.9  872.41   321.5  891.73
   331.8  897.88     366  924.13   393.3  936.65   406.9  940.59   432.3  951.82
#Mann= 3 ,-1,0
       0      .1       0  207.38    .045       0  228.09      .1       0
Bank Sta=207.38,228.09
XS Rating Curve= 0 ,0
Exp/Cntr(USF)=0,0
Exp/Cntr=0.3,0.1

Type RM Length L Ch R = 1 ,1200    ,89.6,89.1,89.8
XS GIS Cut Line= 6
1633358.82337342490435.4419990031633409.37937467490506.818824753
 1633452.7132775 490567.999804751633509.89951484490650.064929336
1633552.31839326490712.0005010071633601.79926543490784.264792174
#Sta/Elev= 30
       0  926.91     8.2   923.5    15.2  919.64    41.9  901.24      62  881.97
    86.1  860.81   102.2  851.57   125.2  832.19   134.3  826.65   138.4  824.88
   147.9  822.82   170.5  822.97   186.5  821.59   197.8818.9054   217.7  818.05
  227.24818.9072   230.5   820.8   234.5  824.31   238.5  825.89   274.4  832.12
   310.2  843.32   320.6  847.82   352.2  866.46     367  879.99   384.5  894.34
   392.3   903.7   396.1  907.41   413.6  921.12   420.6  925.64   425.1  927.65
#Mann= 3 ,-1,0
       0      .1       0   197.8    .045       0  227.24      .1       0
Bank Sta=197.8,227.24
XS Rating Curve= 0 ,0
Exp/Cntr(USF)=0,0
Exp/Cntr=0.3,0.1

Type RM Length L Ch R = 1 ,1111    ,70.8,64.9,63
XS GIS Cut Line= 2
1633293.40348236490491.2621130011633531.31491566490840.667096221
#Sta/Elev= 30
       0  908.38    24.6  900.89    46.6  891.39    75.8  883.57   104.8  872.46
   112.7  867.55   128.6  859.26   134.1  855.51   149.7  841.78   157.4  835.88
     169  822.81   174.9   818.9  177.89818.0681     204  816.97  208.81 818.066
   215.8  820.66   237.1  821.81   248.9  827.18   260.7  831.53   319.1  844.86
     335  849.72   342.9   853.5   353.2  860.14   367.2  863.96   373.1  866.43
   378.6  870.48   394.5  880.08   414.4  889.92   419.7  894.06   422.7  897.48
#Mann= 3 ,-1,0
       0      .1       0  177.89    .045       0  208.81      .1       0
Bank Sta=177.89,208.81
XS Rating Curve= 0 ,0
Exp/Cntr(USF)=0,0
Exp/Cntr=0.3,0.1

Type RM Length L Ch R = 1 ,1046    ,110.7,118.4,117.9
XS GIS Cut Line= 3
1633235.35696239490564.4488036421633324.37622193490670.560814501
1633520.67510195490847.133237303
#Sta/Elev= 30
       0  902.58    36.8  879.41    69.9  870.79    95.4  860.52   105.6  855.46
   122.9  842.87   139.2  834.34   142.2  833.64     152   836.4   158.6  835.19
     163  831.31   169.4  821.91   171.7  819.19  174.74817.0812   176.5  816.24
     181  816.07  194.99817.0786   207.2  817.86   229.2  821.26   245.2  828.54
   274.6  835.88   299.2  844.37   326.3  856.77   352.8  864.81   359.9  869.16
   370.4  878.15   385.5  887.99   392.4  893.91   399.4  898.58   402.5  901.57
#Mann= 3 ,-1,0
       0      .1       0  174.74    .045       0  194.99      .1       0
Bank Sta=174.74,194.99
XS Rating Curve= 0 ,0
Exp/Cntr(USF)=0,0
Exp/Cntr=0.3,0.1

Type RM Length L Ch R = 1 ,927     ,245,239.9,231.3
XS GIS Cut Line= 3
1633225.51240515 490569.208173171633281.99075678490725.661938428
1633333.90376563490963.554565822
#Sta/Elev= 30
       0  903.03    12.7  892.54    19.7  887.64    37.1  878.01    54.7  871.49
    77.7  859.39   103.4  852.43   120.8  844.49   141.8  838.45   159.2  830.66
   178.5  820.37     183  818.72   196.4  816.26   213.2  816.48  221.39814.2537
   228.2     813  234.52814.2532   253.5  817.01   260.2  819.89   266.9  825.73
   270.3  826.69   287.1  827.68   307.2  834.61   327.4   846.2   337.4  853.28
   346.7  857.38   357.6  860.61   367.7  865.09     388  876.93   409.8  885.84
#Mann= 3 ,-1,0
       0      .1       0  221.39    .045       0  234.52      .1       0
Bank Sta=221.39,234.52
XS Rating Curve= 0 ,0
Exp/Cntr(USF)=0,0
Exp/Cntr=0.3,0.1

Type RM Length L Ch R = 1 ,687     ,96.6,87.3,80.2
XS GIS Cut Line= 2
1632974.72506802490644.8949573821633246.87467806490991.666234698
#Sta/Elev= 30
       0  932.67    19.1  925.47    27.4  920.76    34.4  913.86    43.2  900.83
    48.5  895.24    60.8  887.05    85.8  874.66    96.4  866.99   111.5  854.71
   131.7   835.8   144.2  821.33   151.2  810.29  153.44 808.059   165.2  807.19
  176.36808.0623   190.1  811.54   207.3  810.46   231.8  812.49   256.3  809.64
   266.4  811.92   290.1  819.49   305.4  822.94   327.7  831.74   356.8  849.24
   373.6  849.11   381.9  851.29   402.8  860.94   423.6  868.27   440.8  881.77
#Mann= 3 ,-1,0
       0      .1       0  153.44    .045       0  176.36      .1       0
#XS Ineff= 2 , 0
                          229.79          833.51
Permanent Ineff=
       F       F
Bank Sta=153.44,176.36
XS Rating Curve= 0 ,0
Exp/Cntr(USF)=0,0
Exp/Cntr=0.3,0.1