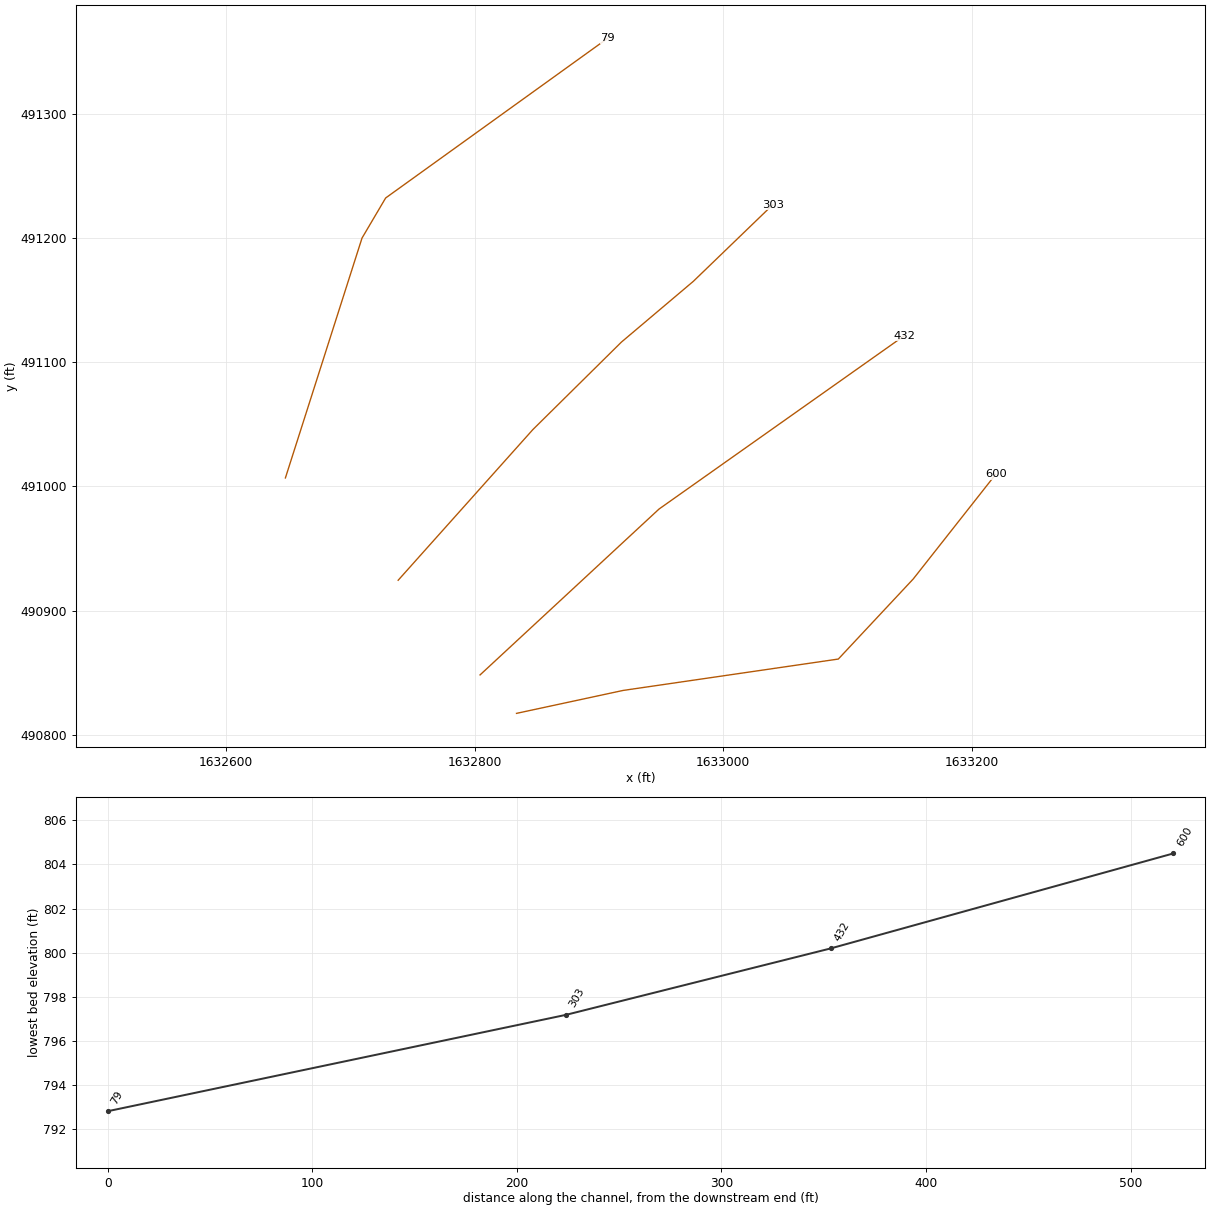
HEC-RAS study GraveCkT3.prj: GraveCkT3

--- GraveCkT3.g01 (geometry) --- (continued)

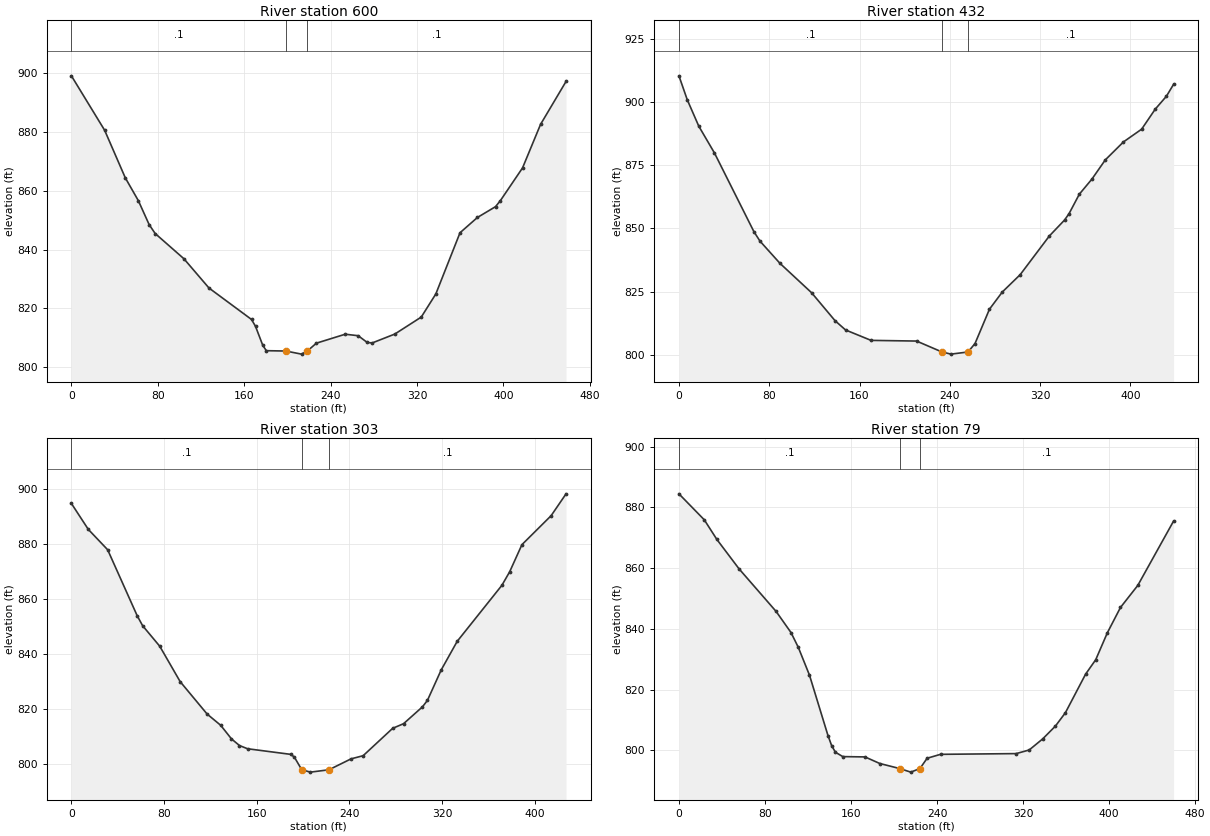
Type RM Length L Ch R = 1 ,600     ,161.4,167.6,171.7
XS GIS Cut Line= 6
1632833.71746826 490817.455670671632919.45253301490835.906093091
1632993.66727959490846.7295622531633092.62049375490861.160307676
1633152.87496643490925.5640502571633219.21276025491009.743671924
#Sta/Elev= 30
       0  898.98    30.8  880.49    49.9  864.36      62   856.6      72  848.47
    77.6  845.44   104.2  836.88   127.4  826.95   166.8  816.27   170.5  813.94
   177.2  807.52   180.5  805.67   198.6  805.55   213.1   804.5   218.5805.5643
   226.9  808.22   253.6  811.26   265.6  810.75     274  808.45   278.6   808.3
   299.5  811.31     324  817.08   337.5  824.93   359.9  845.71     376  850.89
   392.8  854.57   397.3  856.62   417.8  867.72   434.5  882.51   458.1  897.08
#Mann= 3 ,0,0
       0      .1       0   198.6    .045       0   218.5      .1       0
Bank Sta=198.6,218.5
XS Rating Curve= 0 ,0
Exp/Cntr(USF)=0,0
Exp/Cntr=0.3,0.1

Type RM Length L Ch R = 1 ,432     ,127.4,129.3,131
XS GIS Cut Line= 3
1632804.40242932490848.3970230481632948.37835206490981.838122168
1633145.90629483491121.424535062
#Sta/Elev= 30
       0  910.49     7.4  900.97    17.6  890.52    31.5  879.89    66.4  848.74
    71.8  844.98    89.5  836.17   117.5  824.53   138.3  813.44   147.6  809.77
   170.2  805.64   210.5  805.37  233.05801.0421     241  800.19  256.09801.0425
   262.3   804.4   275.1  818.01   286.5  824.83   302.3  831.68   328.2  847.05
   341.6  853.33   345.6  855.87   354.7  863.58   365.9  869.59   377.7  877.17
   393.8   884.3   409.9  889.35   421.9  897.26   431.8  902.37   438.2  907.13
#Mann= 3 ,-1,0
       0      .1       0  233.05    .045       0  256.09      .1       0
Bank Sta=233.05,256.09
XS Rating Curve= 0 ,0
Exp/Cntr(USF)=0,0
Exp/Cntr=0.3,0.1

Type RM Length L Ch R = 1 ,303     ,221.5,224,224.6
XS GIS Cut Line= 6
1632738.51260617490924.5558501781632796.82810634490989.789971679
1632846.81258643491045.7042299211632918.08344126491116.120099589
1632975.93929668491165.002547756 1633039.7416625 491226.54245092
#Sta/Elev= 30
       0  894.86    14.6  885.43    31.3  878.03    56.8  854.04    61.5  850.41
    76.3  842.94    93.9  830.09   117.2  818.29   128.9  814.21   138.2  809.27
   145.1  806.85   152.1  805.68   189.2  803.65   192.4  802.72  198.92798.0276
   206.4  797.18  222.33798.0275   241.5  802.01   251.9  803.15   277.4  813.11
   286.8  814.79   303.1  820.91   307.4  823.26   319.3  834.34   333.1  844.73
   371.7   865.1   378.4  870.01     389  879.88   414.2  890.41   427.1  898.36
#Mann= 3 ,-1,0
       0      .1       0  198.92    .045       0  222.33      .1       0
Bank Sta=198.92,222.33
XS Rating Curve= 0 ,0
Exp/Cntr(USF)=0,0
Exp/Cntr=0.3,0.1

Type RM Length L Ch R = 1 ,79      ,,,
XS GIS Cut Line= 4
1632647.79550481491006.8650737661632709.42659329491199.822219945
1632728.43431216491232.0777428891632906.99167131491360.523843181
#Sta/Elev= 30
       0  884.45    23.6  875.88    35.3  869.42    55.9  859.75    90.4  845.71
   104.2  838.78     111   833.9   121.4  824.74   138.6  804.86     142  801.55
   145.5  799.36   152.4  797.92     173  797.82   186.8  795.65  205.27793.9884
   215.6  792.81  224.11793.9869   230.8  797.38   243.3  798.67   313.6  798.91
   325.7   800.1   338.3  803.76   350.1  807.97   359.4  812.38   378.2  825.09
   387.6  829.83   398.4  838.69   410.6  847.03   426.7  854.29     460  875.49
#Mann= 3 ,-1,0
       0      .1       0  205.27    .045       0  224.11      .1       0
Bank Sta=205.27,224.11
XS Rating Curve= 0 ,0
Exp/Cntr(USF)=0,0
Exp/Cntr=0.3,0.1
LCMann Table=0

Chan Stop Cuts=-1
Use User Specified Reach Order=0
Composite Channel Slope=5